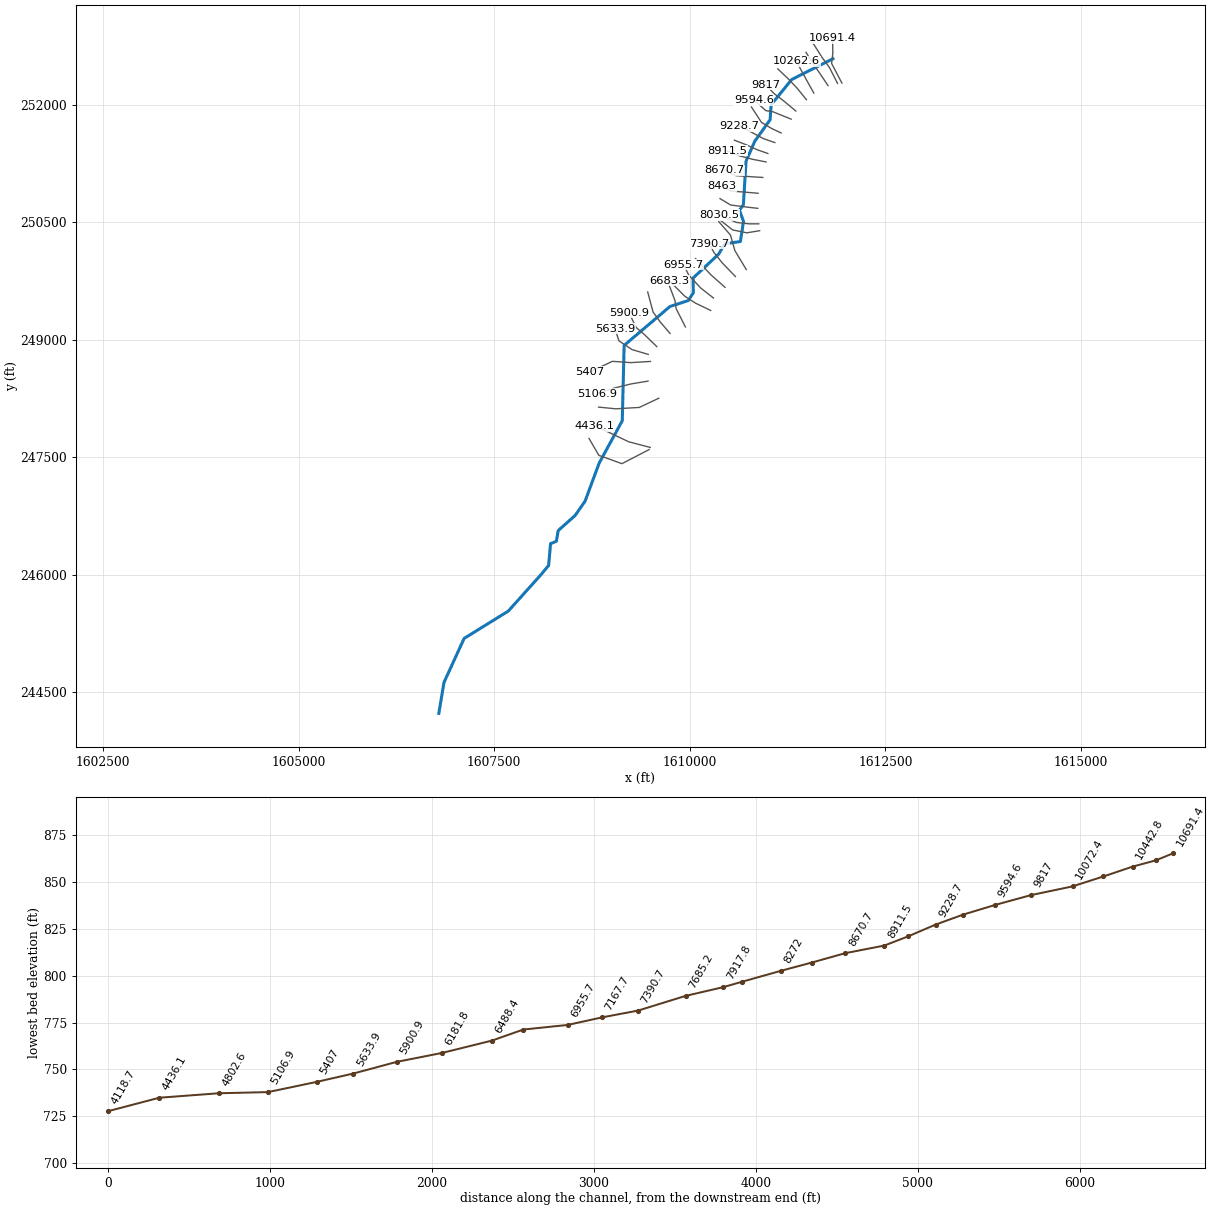
--- sycmrcrk.prj (project) ---

Proj Title=sycmrcrk
Current Plan=p01
Default Exp/Contr=0,0
English Units
Geom File=g01
Flow File=f01
Plan File=p01
BEGIN DESCRIPTION:
END DESCRIPTION:
DSS Export Rating Curves= 0
DSS Export Rating Curve Sorted= 0
DSS Export Volume Flow Curves= 0
DXF OffsetX= 0
DXF OffsetY= 0
DXF ScaleX= 0
DXF ScaleY= 0

--- sycmrcrk.p01 (plan) ---

Plan Title=Floodplain
Program Version=4.00
Geom File=g01
Flow File=f01
K Sum by GR=0
Std Step Tol=0.01
Critical Tol=0.01
Num of Std Step Trials=20
Max Error Tol=0.3
Flow Tol Ratio=0.001
Split Flow NTrial=30
Split Flow Tol=0.02
Split Flow Ratio=0.02
Log Output Level=0
Friction Slope Method=1
Unsteady Friction Slope Method=2
Unsteady Bridges Friction Slope Method=1
Global Log Level=0
CheckData=False
Run HTab=0
Run UNet=0
Run PostProcess=0
UNET Theta=0
UNET Theta Warmup=0
UNET ZTol=0
UNET ZSATol=0
UNET MxIter=0
UNET MaxInSteps=0
UNET DtIC=0
UNET DtMin=0
UNET MaxCRTS=0
UNET WFStab=0
UNET SFStab=0
UNET WFX=0
UNET SFX=0
UNET DSS MLevel=0
UNET DZMax Abort=0
UNET Convert EG Bridges=0
UNET Use Existing IB Tables=0
UNET Froude Limit=0
UNET Froude Power=0
Write IC File=0
Echo Input=False
Echo Output=False
Write Detailed=0

--- sycmrcrk.f01 (steady flow) ---

Flow Title=NFF Regression Equation
Program Version=4.00
Number of Profiles= 1
Profile Names=P100yr
River Rch & RM=sycmrcrk,Main            ,10691.4
     355
River Rch & RM=sycmrcrk,Main            ,9594.6
     374
River Rch & RM=sycmrcrk,Main            ,8911.5
     412
River Rch & RM=sycmrcrk,Main            ,7685.2
     427
River Rch & RM=sycmrcrk,Main            ,7390.7
     517
River Rch & RM=sycmrcrk,Main            ,5633.9
     540
River Rch & RM=sycmrcrk,Main            ,5407
     661
River Rch & RM=sycmrcrk,Main            ,4802.6
     679
River Rch & RM=sycmrcrk,Main            ,3812.2
     742
River Rch & RM=sycmrcrk,Main            ,1192.2
     792
Boundary for River Rch & Prof#=sycmrcrk,Main            , 1
Up Type= 0
Dn Type= 3
Dn Slope=0.010018
DSS Import GetInterval= 0
DSS Import GetPeak= 0
DSS Import FillOption= 0

--- sycmrcrk.g01 (geometry) ---

Geom Title=USGS 10m DEM
Program Version=4.00

River Reach=sycmrcrk        ,Main
Reach XY= 30
     1611829.095      252587.185     1611302.342      252322.353
     1611040.015      252000.221     1611026.189      251807.947
     1610830.658      251534.782     1610718.838      251278.868
     1610684.385      250720.532     1610634.241      250653.134
     1610686.513      250509.097     1610646.766      250253.718
     1610442.328      250221.824     1610369.956      250092.952
     1610042.251      249787.393      1610044.91      249597.867
     1609980.416      249498.978     1609747.485      249423.769
     1609160.719      248926.642      1609136.65      247964.069
     1608841.829      247424.209     1608661.292       246936.84
     1608534.119      246753.704     1608318.178      246561.801
     1608294.212      246424.828     1608220.132      246393.773
     1608195.291      246115.853     1608100.482      246001.137
     1607679.036      245532.372     1607115.223      245183.638
     1606857.509      244620.648     1606791.562      244226.575

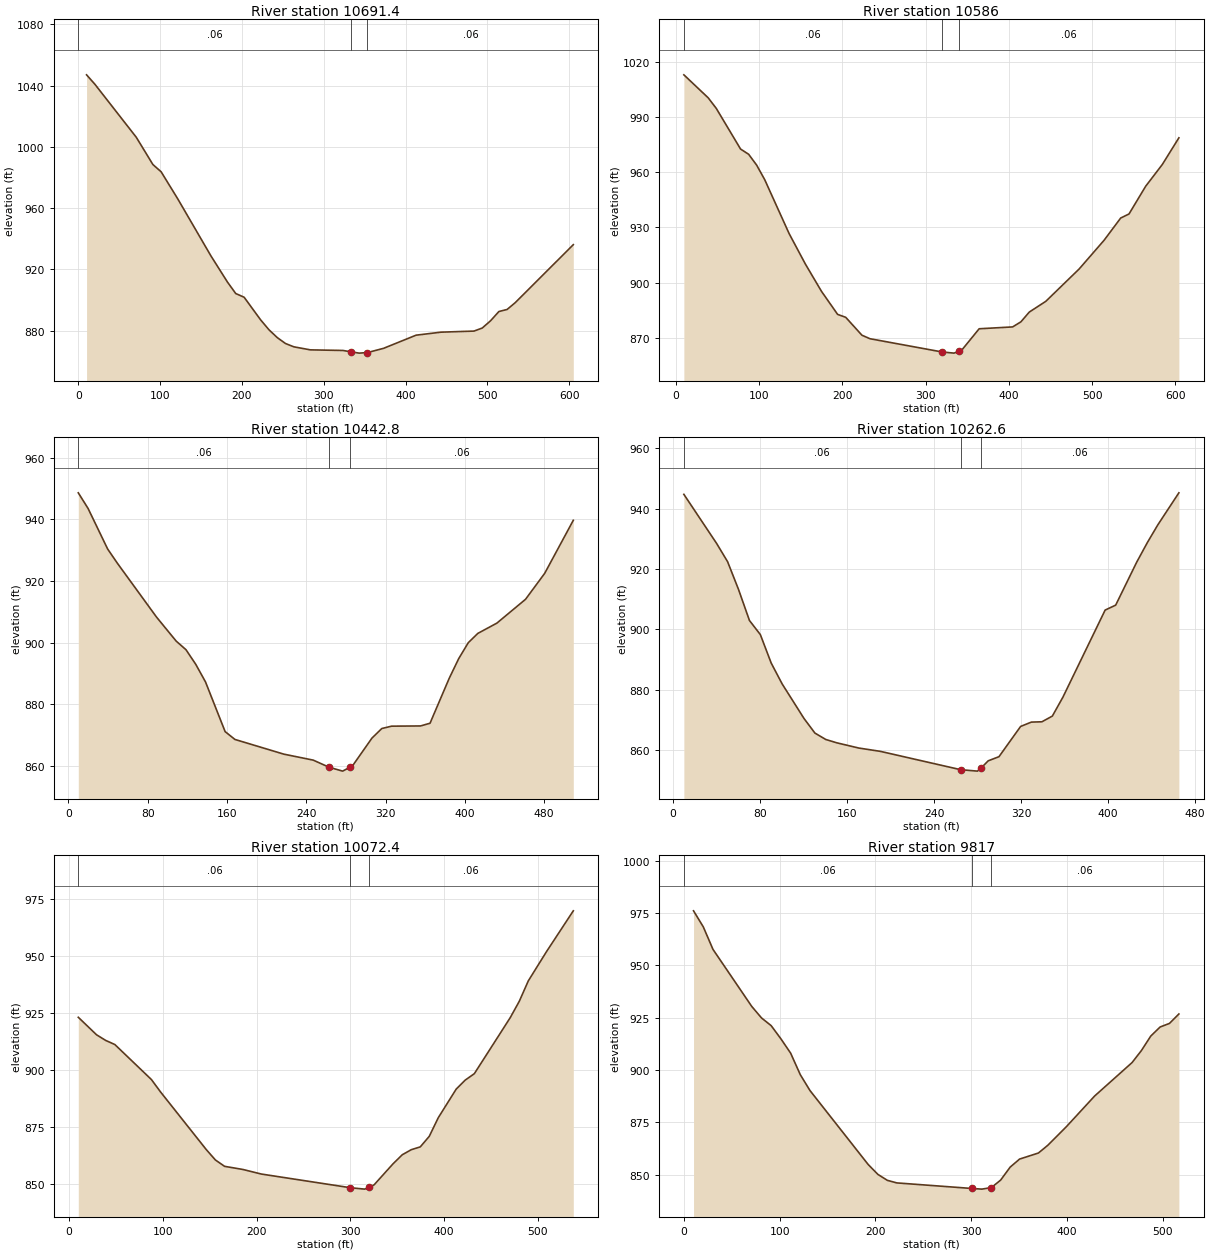
Type RM Length L Ch R = 1 ,10691.4 ,90.3,105.5,120.6
XS GIS Cut Line= 4
     1611944.015      252276.397     1611812.464      252527.792
     1611827.827      252656.071     1611825.437      252848.233
#Sta/Elev= 30
    10.1 1046.97    20.3 1040.82    70.9 1006.23    91.2  988.45   101.3   983.7
   121.6  966.04   162.1  928.88   182.4  911.74   192.5  904.28   202.7  901.89
   222.9  887.12   233.1  880.65   243.2  875.56   253.3  871.69   263.5  869.53
   283.7  867.55   323.5  867.16   333.4  866.26   343.4  865.42   353.4  865.77
   373.2  868.55   412.9  877.13   443.3  879.09   483.7   879.8   493.8  881.79
     504  886.55   514.1  892.54   524.2  893.91   534.3  898.44   605.1  936.18
#Mann= 3 , 0 , 0
       0     .06       0   333.4    .045       0   353.4     .06       0
Bank Sta=333.4,353.4
XS Rating Curve= 0 ,0
Exp/Cntr=0.3,0.1

Type RM Length L Ch R = 1 ,10586   ,143.5,143.2,142.8
XS GIS Cut Line= 4
     1611888.254      252273.325     1611781.739      252480.892
     1611691.611      252602.429     1611574.171      252788.148
#Sta/Elev= 30
     9.7 1012.87    38.9 1000.39    48.6  994.66    77.8  972.56    87.5  969.71
    97.2  963.77   106.9  955.83   136.1  926.65   155.5   910.2     175  895.25
   194.4  882.72   204.1  881.14   223.6  871.41   233.3   869.5  320.01   862.3
   334.2  861.68  340.39  862.74   344.3  863.76   364.4  874.91   404.6  875.92
   414.6   878.7   424.6  883.98   444.5  889.84   484.5  907.39   514.5  923.02
   534.4  935.07   544.4  937.28   564.4  952.33   584.4  964.16   604.3  978.64
#Mann= 3 , 0 , 0
     9.7     .06       0  320.01    .045       0  340.39     .06       0
Bank Sta=320.01,340.39
XS Rating Curve= 0 ,0
Exp/Cntr=0.3,0.1

Type RM Length L Ch R = 1 ,10442.8 ,182.5,180.2,178
XS GIS Cut Line= 4
     1611766.718      252244.647     1611645.181      252424.904
     1611576.902       252521.86     1611485.408      252669.342
#Sta/Elev= 30
     9.9  948.59    19.8  943.51    39.5  930.39    49.4  925.74    88.9  908.28
   108.7  900.51   118.6  897.72   128.5  892.96   138.3  887.27   158.1  871.16
     168  868.62   217.4  863.85     247  861.92  262.88  859.63   276.7  858.35
  283.65  859.53   286.7  860.08   306.3  869.06   316.2  872.16   326.1  872.93
   355.3     873   364.9  873.88   384.2   888.4   393.8   894.8   403.5  899.99
   413.1     903   432.4  906.35   461.3  914.07   480.6  922.47   509.5  939.68
#Mann= 3 , 0 , 0
     9.9     .06       0  262.88    .045       0  283.65     .06       0
Bank Sta=262.88,283.65
XS Rating Curve= 0 ,0
Exp/Cntr=0.3,0.1

Type RM Length L Ch R = 1 ,10262.6 ,185,190.2,195.3
XS GIS Cut Line= 4
     1611585.096      252149.057     1611492.236      252315.658
     1611425.323      252437.194     1611362.506      252557.365
#Sta/Elev= 30
      10  944.69    40.2  928.39    50.2   922.4    60.2  913.26    70.3  902.94
    80.3  898.28    90.3  888.84   100.4  881.92   120.5  870.48   130.5  865.67
   140.5  863.55   150.6  862.45   170.7  860.73   190.7  859.62  264.55  853.55
   279.9  853.08  282.88  853.96   289.8  856.49   299.7  857.86   319.6  867.87
   329.5  869.31   339.2  869.41   348.8  871.31   358.5  877.57   397.3  906.38
     407  908.02   426.3  922.22     436  928.65   445.7  934.57   465.1  945.19
#Mann= 3 , 0 , 0
      10     .06       0  264.55    .045       0  282.88     .06       0
Bank Sta=264.55,282.88
XS Rating Curve= 0 ,0
Exp/Cntr=0.3,0.1

Type RM Length L Ch R = 1 ,10072.4 ,252.2,255.4,258.6
XS GIS Cut Line= 4
     1611490.871      252064.391     1611367.969       252215.97
     1611257.357      252332.045     1611124.896      252457.678
#Sta/Elev= 30
     9.8  923.04    29.3  915.37      39  912.92    48.8  911.11    87.8  895.79
    97.6  890.33   146.4  865.09   156.1  860.56   165.9  857.77   185.4   856.4
   205.2  854.39  300.22   848.4   315.4  847.79  320.09  848.58   325.4  849.65
   345.5  858.81   355.5  862.84   365.1  865.06   374.7  866.29   384.3   870.9
   393.9  879.05   413.1  891.62   422.7  895.54   432.4  898.35   461.2  916.78
   470.8  922.95   480.4  930.08     490  938.99   509.2  951.66     538  969.66
#Mann= 3 , 0 , 0
     9.8     .06       0  300.22    .045       0  320.09     .06       0
Bank Sta=300.22,320.09
XS Rating Curve= 0 ,0
Exp/Cntr=0.3,0.1

Type RM Length L Ch R = 1 ,9817    ,212.5,222.4,232.3
XS GIS Cut Line= 4
     1611355.678       251919.64     1611200.002       252049.37
     1611074.369       252144.96     1610966.489      252258.303
#Sta/Elev= 30
    10.1  976.01    20.3  968.34    30.4  957.61    70.9  930.37    81.1  924.87
    91.2  921.18   101.3  914.93   111.5  908.07   121.6  897.78   131.7  890.22
   192.5   854.9   202.6   850.2   212.5  847.34   222.4  846.11   301.2  843.44
   311.2  843.14   321.2  843.88   330.9  847.48   340.8  853.65   350.6  857.48
   370.3  860.38   380.1  864.07   399.6     873     429  887.59   468.1  903.56
   477.9  909.32   487.6  916.19   497.4  920.55   507.2  922.26     517  926.76
#Mann= 3 , 0 , 0
       0     .06       0   301.2    .045       0   321.2     .06       0
Bank Sta=301.2,321.2
XS Rating Curve= 0 ,0
Exp/Cntr=0.3,0.1

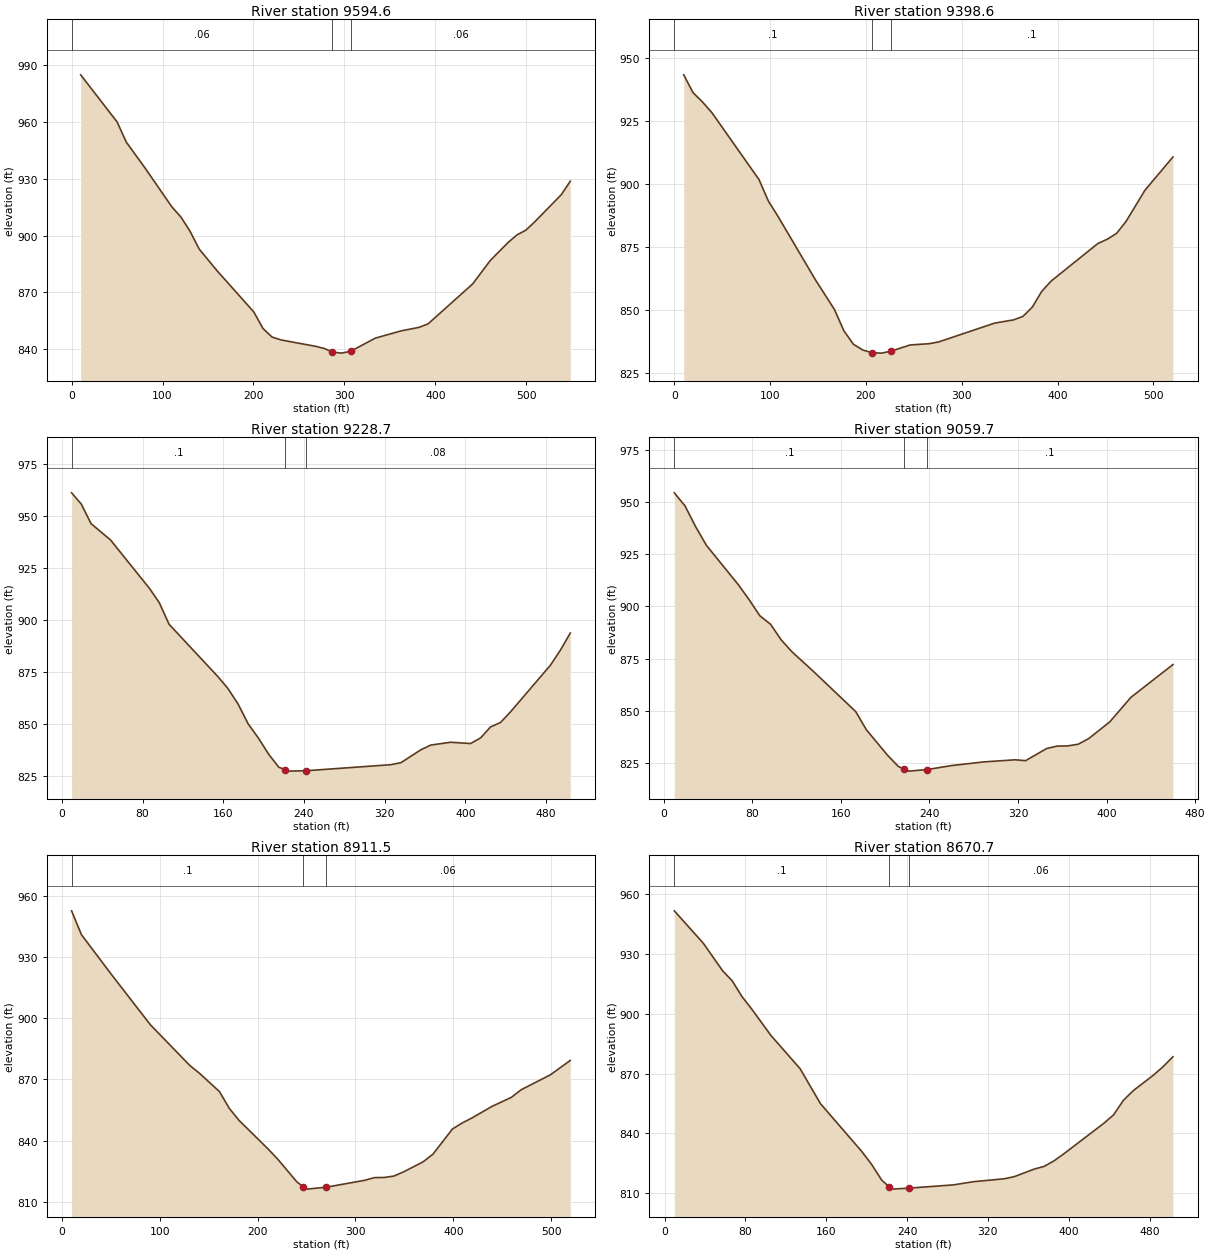
Type RM Length L Ch R = 1 ,9594.6  ,203.5,196,188.4
XS GIS Cut Line= 4
     1611295.593      251815.856     1611063.445      251910.081
     1610971.951      251925.102      1610817.64      252060.294
#Sta/Elev= 30
      10  984.89    50.1  959.97    60.1  949.38    80.2  936.07   110.2  915.19
   120.3  909.73   130.3  902.22   140.3  892.87   160.3  881.22   200.4  859.62
   210.5  850.87   220.5  846.35   230.5  844.83   269.1   841.4   278.4  840.24
   286.9  838.42   296.9  837.87   306.9  838.86     334  845.79   362.8  849.67
   382.3  851.51   392.1  853.35     441  874.39   460.5  886.84     480  896.29
   489.8  900.32   499.6  902.85   509.3  907.21   538.6  921.61   548.4  928.69
#Mann= 3 , 0 , 0
       0     .06       0   286.9    .045       0   306.9     .06       0
Bank Sta=286.9,306.9
XS Rating Curve= 0 ,0
Exp/Cntr=0.3,0.1

Type RM Length L Ch R = 1 ,9398.6  ,168.9,169.9,170.9
XS GIS Cut Line= 4
     1611167.229      251639.696     1611042.961      251698.416
     1610915.962      251774.888     1610787.598      251971.532
#Sta/Elev= 30
     9.8   943.5    19.6  936.39    29.5  932.68    39.3  928.42    88.4  901.82
    98.2  893.26     108  887.31   147.3  861.91   167.1  850.14     177  841.64
   186.9  836.28   196.7  833.98   206.5  832.88   216.5  832.73   226.5  833.55
   246.2  835.98   265.9  836.48   275.8  837.17   334.6   844.7   354.2  845.96
     364  847.37   373.8   851.1   383.5  857.29   393.3   861.4   442.2  876.38
     452  878.08   461.8  880.45   471.6  885.18   491.2  897.53   520.5  910.81
#Mann= 3 , 0 , 0
       0      .1       0   206.5    .045       0   226.5      .1       0
Bank Sta=206.5,226.5
XS Rating Curve= 0 ,0
Exp/Cntr=0.3,0.1

Type RM Length L Ch R = 1 ,9228.7  ,167.6,169,170.4
XS GIS Cut Line= 4
      1611086.66      251516.794     1610940.543       251567.32
      1610780.77      251653.352     1610629.191      251725.728
#Sta/Elev= 30
     9.7  961.25    19.3  955.84      29  946.43    48.3  938.58      87  915.22
    96.6  908.45   106.3  898.06   154.6  872.93   164.7  867.14   174.8  859.61
   184.8  850.09   194.9  843.32     205  835.57   215.1  829.29  221.33  828.12
   225.2  827.41  242.38   827.6     326   830.5   336.1  831.46   355.8  837.63
   365.7  839.94   385.5   841.3   405.2  840.67   415.1  843.38     425  848.66
   434.9  850.81   444.8  855.92   484.3  878.32   494.2  885.56     504   893.8
#Mann= 3 , 0 , 0
     9.7      .1       0  221.33    .045       0  242.38     .08       0
Bank Sta=221.33,242.38
XS Rating Curve= 0 ,0
Exp/Cntr=0.3,0.1

Type RM Length L Ch R = 1 ,9059.7  ,144.8,148.2,151.6
XS GIS Cut Line= 4
     1610997.897      251377.505     1610861.339        251425.3
     1610712.491      251492.214     1610570.471      251546.837
#Sta/Elev= 30
     9.6  954.34    19.3  948.07    28.9   938.1    38.6  929.22    67.5  910.31
    77.2  903.18    86.8  895.54    96.5  891.46   106.1  883.99   115.7  878.35
     135     869   173.5  849.61   183.1  840.93   202.3  828.69   211.9  823.41
  217.34  822.07   221.5  821.14  237.94  821.88   259.9  823.79   288.7  825.53
   317.4  826.56   326.9  826.15   345.9  831.96   355.4  833.12   364.9  833.22
   374.4  834.01     384  836.74     403  844.76     422  856.44     460  872.15
#Mann= 3 , 0 , 0
     9.6      .1       0  217.34    .045       0  237.94      .1       0
Bank Sta=217.34,237.94
XS Rating Curve= 0 ,0
Exp/Cntr=0.3,0.1

Type RM Length L Ch R = 1 ,8911.5  ,237,240.8,244.6
XS GIS Cut Line= 4
     1610974.682      251269.624     1610806.716      251302.398
     1610634.653      251347.462     1610476.246      251410.279
#Sta/Elev= 30
    10.1  952.65    20.1     941    50.3  921.74    90.6  896.75   130.9  876.78
   140.9   872.9   161.1     864   171.1  855.82     181  849.94   210.7  835.89
   220.5  830.95   240.3  819.63  246.79  817.39   250.2  816.16   269.9  817.09
   309.5  820.49   319.4  821.81   329.2  821.87   339.1  822.54     349  824.58
     369  829.52   379.1  833.26   399.1  845.66   409.1  848.62   419.2  851.11
   439.2  856.67   459.3  861.19   469.3   864.9   499.4  872.31   519.4  879.26
#Mann= 3 , 0 , 0
    10.1      .1       0  246.79    .045       0   269.9     .06       0
Bank Sta=246.79,269.9
XS Rating Curve= 0 ,0
Exp/Cntr=0.3,0.1

Type RM Length L Ch R = 1 ,8670.7  ,208.2,207.7,207.2
XS GIS Cut Line= 4
     1610932.349      251071.616     1610798.522      251079.809
     1610586.858       251094.83     1610446.203      251164.475
#Sta/Elev= 30
     9.6  951.66    38.3  935.42    57.5  921.56      67  916.51    76.6  908.64
    86.2  902.42   105.3  889.14   134.1  872.51   154.3  854.95   194.7  831.27
   204.8  824.59   214.9  816.62  222.31  813.24     225   812.1  241.96   812.6
   285.6  814.22   305.9  815.83   336.2  817.29   346.3  818.38   365.9  822.15
   375.7  823.51   385.5  826.28   395.3  829.85   434.6  845.04   444.4  849.32
   454.2  856.66     464  861.52   483.6  869.15   493.4  873.48   503.2  878.49
#Mann= 3 , 0 , 0
     9.6      .1       0  222.31    .045       0  241.96     .06       0
Bank Sta=222.31,241.96
XS Rating Curve= 0 ,0
Exp/Cntr=0.3,0.1

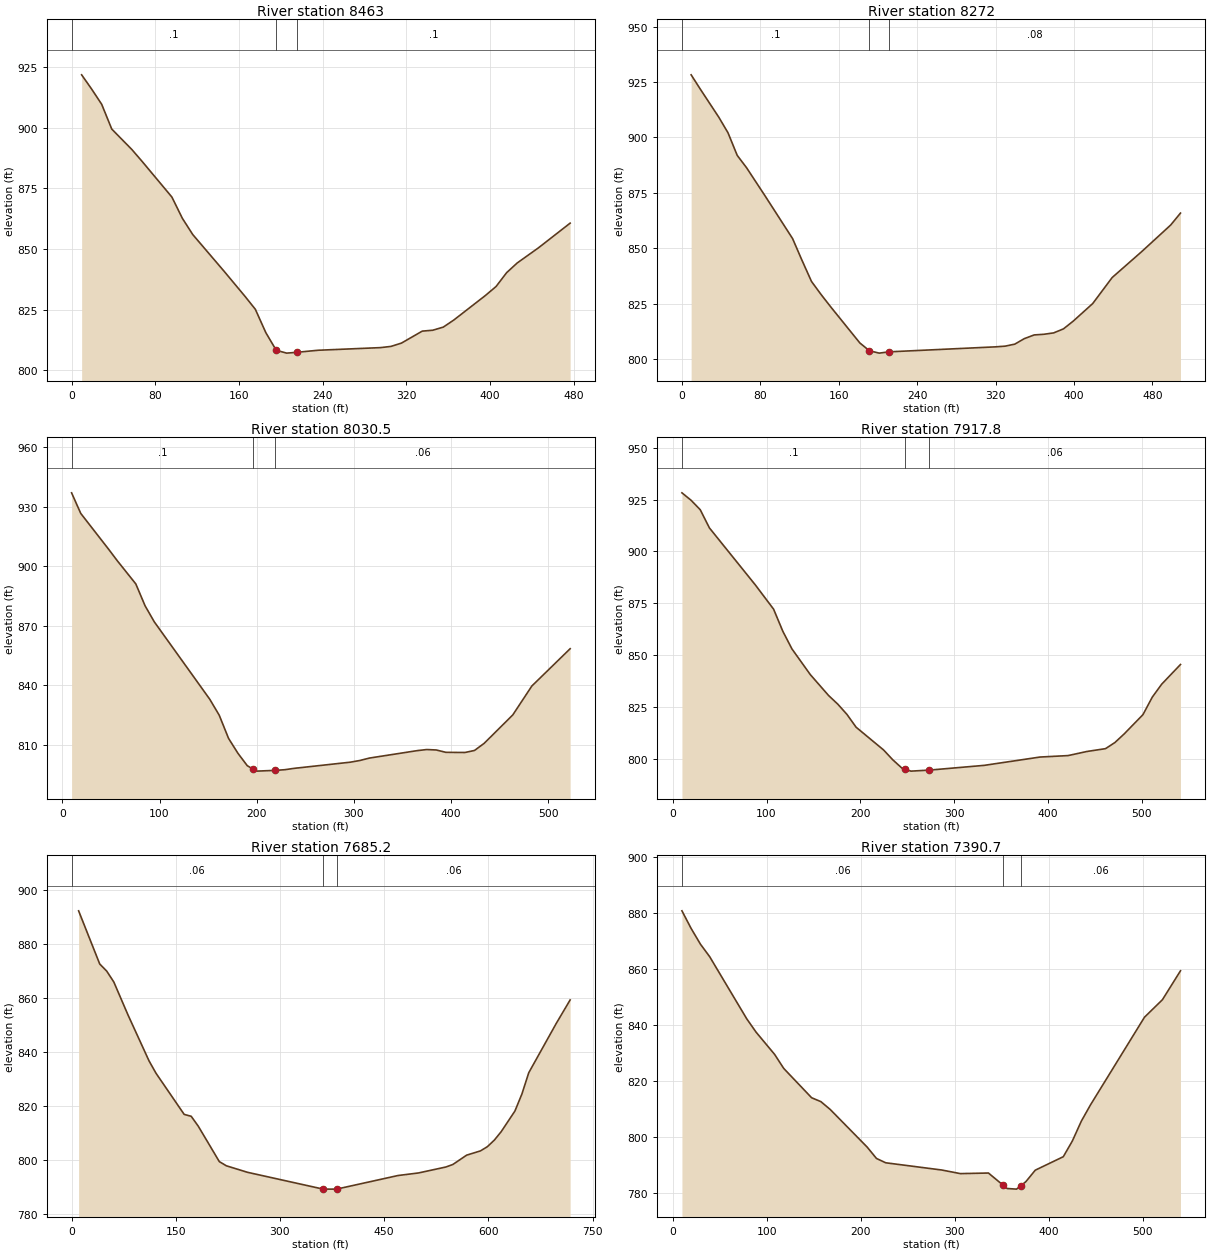
Type RM Length L Ch R = 1 ,8463    ,191.9,190.9,190.6
XS GIS Cut Line= 4
     1610872.264       250869.51     1610776.673      250877.703
     1610528.138      250898.187     1610412.064      250959.638
#Sta/Elev= 30
     9.6  921.76    19.2  915.87    28.8   909.6    38.4  899.41    57.6  890.99
    67.2   886.2    95.9  871.39   105.9  862.64   115.9  855.91   145.8  840.82
   165.8  830.48   175.7  825.14   185.7  815.53   195.7  808.23   205.7  807.07
   215.7  807.42   235.6  808.25   295.4  809.34   305.4  809.84   315.4   811.2
   335.3  816.14   345.3   816.5   355.4  817.79   365.5  820.72   395.8  830.86
   405.9  834.54     416  840.24   426.1  844.23   446.3  850.43   476.7  860.64
#Mann= 3 , 0 , 0
       0      .1       0   195.7    .045       0   215.7      .1       0
Bank Sta=195.7,215.7
XS Rating Curve= 0 ,0
Exp/Cntr=0.3,0.1

Type RM Length L Ch R = 1 ,8272    ,239.6,241.5,241.9
XS GIS Cut Line= 4
     1610869.532      250676.963     1610747.996      250690.619
     1610522.676      250719.296     1610386.118      250801.231
#Sta/Elev= 30
     9.4  928.25    18.8  921.76    37.6  909.13      47   902.1    56.4   891.9
    65.9  886.35    84.7   873.7   112.9  854.34   122.3  844.74   132.2  834.99
   142.1  829.03   151.9  823.47   181.6   807.2   191.3  803.71   201.3  802.64
   211.3  803.22   319.8  805.47   329.7  805.78   339.6  806.69   349.4  809.19
   359.4  810.85   369.3  811.15   379.3  811.77   389.3  813.59   399.2  817.06
   419.1  824.99     439  836.76   468.9  848.37   498.7  860.46   508.7  865.84
#Mann= 3 , 0 , 0
       0      .1       0   191.3    .045       0   211.3     .08       0
Bank Sta=191.3,211.3
XS Rating Curve= 0 ,0
Exp/Cntr=0.3,0.1

Type RM Length L Ch R = 1 ,8030.5  ,114.6,112.7,110.8
XS GIS Cut Line= 4
     1610881.823      250478.954     1610758.921      250478.954
     1610596.417      250496.707     1610380.656      250592.298
#Sta/Elev= 30
     9.5  936.96    18.9  926.61    47.3  908.73    56.7  902.63    75.6  891.04
    85.1  880.05    94.5  872.02   151.7  832.93   161.4  824.91     171  813.23
   180.6  805.76   190.2  799.51  196.32  797.68   199.8  796.75   219.1  797.13
   228.7  797.46   238.3  798.14   296.2  801.25     306   802.1   315.9  803.33
     365  807.07   374.9  807.63   384.7   807.4   394.5  806.22   414.2  806.14
     424  807.16   433.9  810.73   463.4  825.07     483  839.63   522.4  858.42
#Mann= 3 , 0 , 0
     9.5      .1       0  196.32    .045       0   219.1     .06       0
Bank Sta=196.32,219.1
XS Rating Curve= 0 ,0
Exp/Cntr=0.3,0.1

Type RM Length L Ch R = 1 ,7917.8  ,255,232.6,210.3
XS GIS Cut Line= 4
     1610892.747      250391.557     1610728.878      250364.246
     1610547.256      250401.116     1610398.408      250518.556
#Sta/Elev= 30
     9.8  928.31    19.5  924.74    29.3  920.16    39.1  911.36      88  883.86
   107.5  872.13   117.3  861.49     127  852.98   146.6  840.55   166.1  830.44
   175.9  826.28   185.6  821.36   195.4  815.15   224.7  804.16   234.4  799.45
   244.2  795.41  247.72  794.86   253.9  793.94   273.4  794.43   331.9  796.72
   391.4  800.74   421.3  801.44   441.3  803.42   461.2  804.79   471.2  807.74
   481.2  811.95   501.1  821.21   511.1   829.7   521.1  835.93   541.1  845.42
#Mann= 3 , 0 , 0
     9.8      .1       0  247.72    .045       0   273.4     .06       0
Bank Sta=247.72,273.4
XS Rating Curve= 0 ,0
Exp/Cntr=0.3,0.1

Type RM Length L Ch R = 1 ,7685.2  ,286.3,294.5,302.4
XS GIS Cut Line= 4
      1610722.05      249894.487     1610575.933       250137.56
     1610519.944      250335.569     1610369.731      250507.632
#Sta/Elev= 30
    10.1  892.12    40.5  872.48    50.6  869.83    60.8  865.82      81  853.77
   111.4  836.72   121.5  832.11   162.1  816.89   172.2  816.19   182.3  812.57
   212.7  799.44   222.8   797.9   253.2  795.49   361.8   789.3   371.8  789.27
   381.8  789.29   469.8  794.29   499.3  795.24     539  797.45     549  798.39
   568.8  801.83   588.7   803.4   598.6  804.95   608.6  807.37   618.5  810.49
   638.3  818.14   648.3  824.39   658.2  832.28   697.9  850.56   717.8  859.19
#Mann= 3 , 0 , 0
       0     .06       0   361.8    .045       0   381.8     .06       0
Bank Sta=361.8,381.8
XS Rating Curve= 0 ,0
Exp/Cntr=0.3,0.1

Type RM Length L Ch R = 1 ,7390.7  ,221.3,223,224.6
XS GIS Cut Line= 4
     1610582.761      249805.724     1610412.064      249983.249
     1610306.914      250115.711      1610249.56      250226.323
#Sta/Elev= 30
     9.9   880.8    19.7  874.49    29.6  868.88    39.4  864.42    78.8  842.23
    88.7  837.48   108.4  829.54   118.2  824.48   147.8  814.03   157.6  812.65
   167.5  809.87   206.9  796.39   216.7  792.36   226.6   790.8   286.1  788.22
     306  786.93   335.8  787.14  351.63  782.74   355.7  781.61   365.7  781.39
  369.95  782.53   375.6  784.06   385.6  788.16   415.4  792.97     425  798.57
   434.6  805.69   444.2  811.42   501.7  842.79   520.8  849.05     540  859.38
#Mann= 3 , 0 , 0
     9.9     .06       0  351.63    .045       0  369.95     .06       0
Bank Sta=351.63,369.95
XS Rating Curve= 0 ,0
Exp/Cntr=0.3,0.1

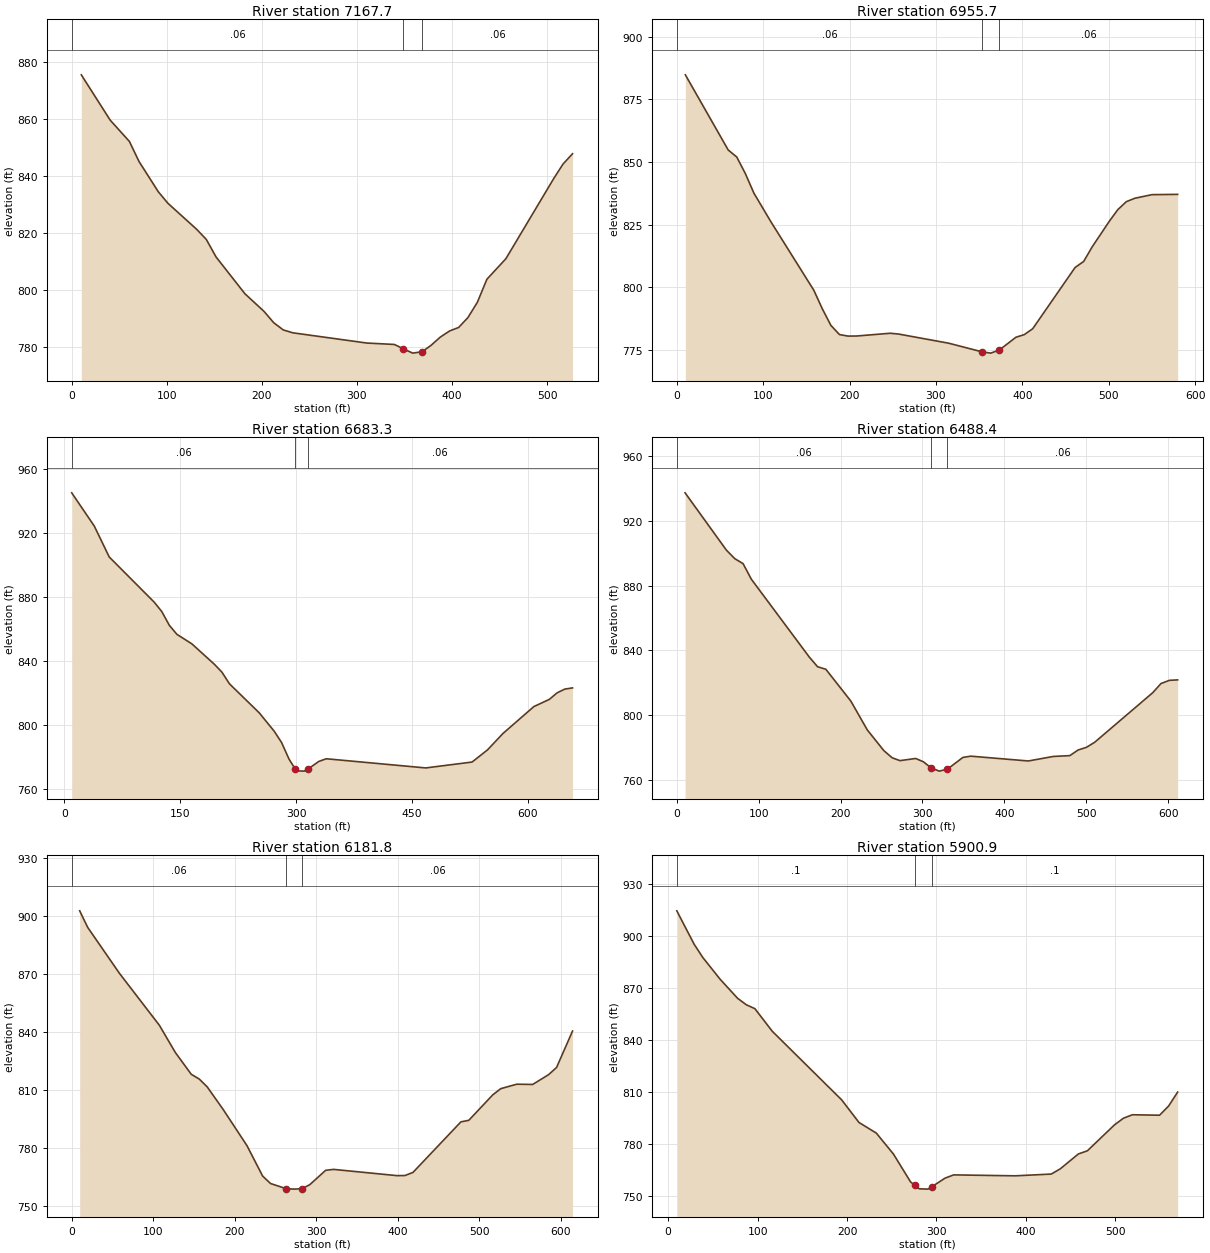
Type RM Length L Ch R = 1 ,7167.7  ,219.7,212,211.3
XS GIS Cut Line= 4
       1610450.3      249667.801     1610268.678      249828.939
     1610149.873      249955.938       1610073.4      250035.141
#Sta/Elev= 30
    10.1  875.64    40.5  859.69    60.7  852.21    70.8  845.15    91.1   834.5
   101.2  830.45   131.5  821.28   141.6  817.73   151.8  811.59   182.1  798.66
   202.3  792.42   212.5  788.43   222.6  785.89   232.7  784.88   310.4  781.29
   339.4  780.79   348.7  779.28   358.7  777.74   368.7  778.25   378.1  780.51
   387.7  783.38   397.4  785.52     407  786.77   416.7  790.22   426.7  795.63
   436.7  803.72   456.7  810.96   506.8  839.04   516.8  844.25   526.8  847.88
#Mann= 3 , 0 , 0
       0     .06       0   348.7    .045       0   368.7     .06       0
Bank Sta=348.7,368.7
XS Rating Curve= 0 ,0
Exp/Cntr=0.3,0.1

Type RM Length L Ch R = 1 ,6955.7  ,259.5,272.5,278.5
XS GIS Cut Line= 4
     1610302.818      249531.243     1610138.948      249659.607
     1609987.369      249823.477     1609920.456      249955.938
#Sta/Elev= 30
     9.9  884.76    59.5  854.77    69.4  851.97    79.3  845.39    89.2  837.59
     109  826.08   158.6  798.81   168.5  791.36   178.4  784.76   188.3  781.11
   198.2   780.5   208.2  780.53     247  781.63   256.7  781.32   314.9  777.65
   353.4  774.21   363.4   773.7   373.4  774.94   392.6  780.04   402.3  781.09
     412  783.43   461.1  807.88     471  810.28   480.9  816.12   500.6  826.27
   510.5  830.94   520.4  834.14   530.3  835.51   550.1  836.94   579.8  837.06
#Mann= 3 , 0 , 0
       0     .06       0   353.4    .045       0   373.4     .06       0
Bank Sta=353.4,373.4
XS Rating Curve= 0 ,0
Exp/Cntr=0.3,0.1

Type RM Length L Ch R = 1 ,6683.3  ,211.9,194.8,177.7
XS GIS Cut Line= 4
     1610266.896      249372.447     1610074.349      249465.306
     1609936.426      249554.069     1609738.417      249752.078
#Sta/Elev= 30
     9.7  945.37    38.9   924.6    58.3  905.21   116.6   876.9   126.3  871.06
     136  862.51   145.8  856.85   165.2  850.88   194.3  838.13   204.1  833.19
   213.8  825.91   252.4  807.72   271.7  796.27   281.3  789.15     291   778.7
  298.65  772.85   300.6  771.45   310.2  771.26  315.01  772.41   329.5  777.34
   339.2  778.99   467.8  773.26   527.8  776.94   547.8  784.56   567.8  794.83
   607.8  811.66   627.8  816.15   637.8  820.22   647.8  822.58   657.8  823.34
#Mann= 3 , 0 , 0
     9.7     .06       0  298.65    .045       0  315.01     .06       0
#XS Ineff= 2 , 0
       0                     339       0
Permanent Ineff=
       F       F
Bank Sta=298.65,315.01
XS Rating Curve= 0 ,0
Exp/Cntr=0.3,0.1

Type RM Length L Ch R = 1 ,6488.4  ,297.2,306.7,316.1
XS GIS Cut Line= 4
      1609943.68      249162.169     1609824.875      249396.707
     1609809.512      249501.174     1609723.481      249728.543
#Sta/Elev= 30
    10.1  937.47    60.7  901.93    70.8  896.76    80.9  893.68      91  884.06
   161.8  835.87   171.9  829.91     182  828.33   212.4  808.76   232.6  790.84
   252.8  778.03   262.9  773.61   272.5  771.82   291.7  773.16   301.3  771.06
   310.5  767.32   320.5  765.33   330.5  766.55   349.3  773.79   358.9  774.59
   429.3  771.61   459.7   774.4   479.9  774.92   490.1  778.41   500.2  780.04
   510.3  783.18   581.2  813.85   591.3  819.52   601.5  821.48   611.6  821.77
#Mann= 3 , 0 , 0
       0     .06       0   310.5    .045       0   330.5     .06       0
Bank Sta=310.5,330.5
XS Rating Curve= 0 ,0
Exp/Cntr=0.3,0.1

Type RM Length L Ch R = 1 ,6181.8  ,276.1,280.9,285.7
XS GIS Cut Line= 4
     1609747.027      249079.237     1609620.028      249228.085
       1609529.9      249353.718     1609461.621      249609.081
#Sta/Elev= 30
     9.8  902.56    19.6  894.02    58.7  870.21   107.6  843.42   127.2  829.35
   146.7   818.1   156.5  815.65   166.3  811.59   185.9   799.9     215  781.29
   234.3  765.52     244  761.66     263  759.02     273  758.76     283  759.01
   292.3  761.12   311.6  768.47   321.3  768.96   399.2  765.73     409  765.79
   418.8   767.4   477.6  793.51   487.3  794.32   516.7  807.47   526.5  810.67
   546.1  812.97   565.7  812.85   585.2   817.9     595  821.62   614.6  840.44
#Mann= 3 , 0 , 0
       0     .06       0     263    .045       0     283     .06       0
Bank Sta=263,283
XS Rating Curve= 0 ,0
Exp/Cntr=0.3,0.1

Type RM Length L Ch R = 1 ,5900.9  ,264.6,267,269.4
XS GIS Cut Line= 4
     1609577.695       248911.27     1609424.751      249060.119
     1609315.504      249154.343     1609221.279      249344.159
#Sta/Elev= 30
     9.7  914.41    29.1  895.14    38.8  887.49    58.2  874.93    77.6  864.01
    87.3  860.29      97  857.99   116.4  844.99     194  805.42   213.4  792.37
   232.7  786.29   251.9  774.18   271.1  758.07  275.49  756.32   280.7  754.15
   290.4  753.96  294.82  755.33   309.6   760.3   319.2  762.17     388  761.63
   428.3  762.64   438.4  765.66   458.6  774.23   468.7  776.06     499  791.01
   509.1  794.87   519.1  796.84   549.4  796.57   559.5  801.86   569.6   809.9
#Mann= 3 , 0 , 0
     9.7      .1       0  275.49    .045       0  294.82      .1       0
Bank Sta=275.49,294.82
XS Rating Curve= 0 ,0
Exp/Cntr=0.3,0.1

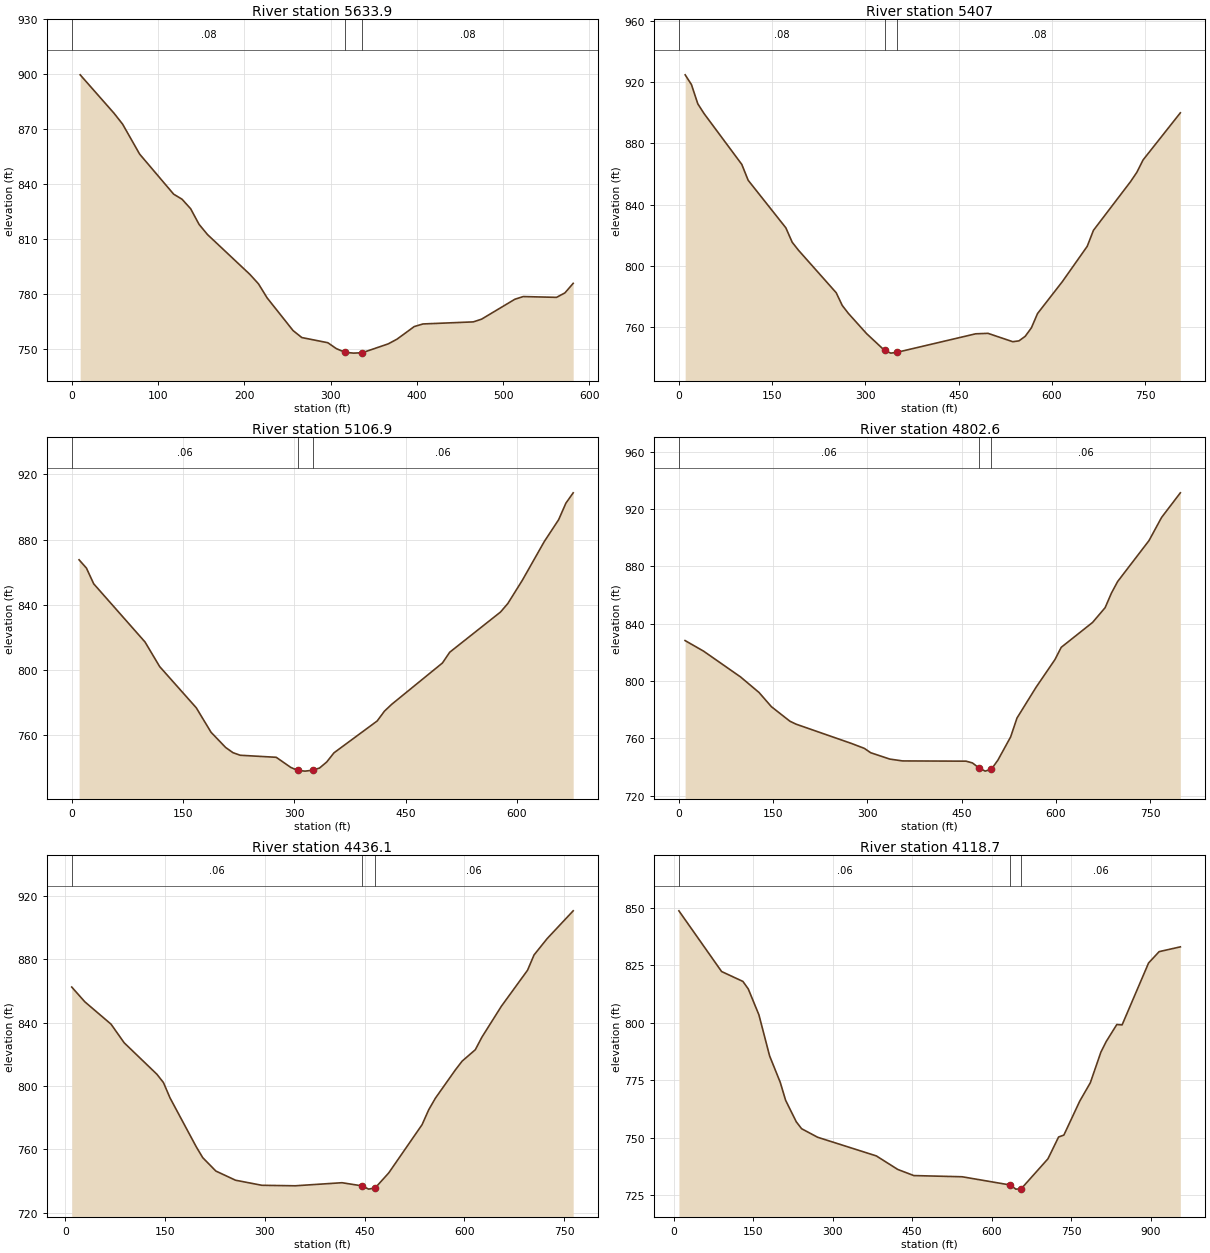
Type RM Length L Ch R = 1 ,5633.9  ,216.2,226.9,237.5
XS GIS Cut Line= 4
     1609468.449      248811.583     1609260.881      248873.034
      1609094.28      248985.012     1609042.389      249140.688
#Sta/Elev= 30
     9.8  899.63    49.2  878.57      59  872.69    78.7  856.37   118.1  834.52
   127.9  831.72   137.8  826.58   147.6  818.03   157.4  812.44   206.6  790.68
   216.5  785.55   226.5   777.9   256.6  760.04   266.7  756.24   296.8  753.43
   306.8  750.18   316.9  748.16   326.9  747.74   336.9  747.97     367  752.81
   377.1  755.37   397.1  762.25   407.2  763.66   465.5  764.79   475.1  766.27
   513.7  777.15   523.4  778.61     562  778.18   571.7  780.61   581.3  785.82
#Mann= 3 , 0 , 0
       0     .08       0   316.9    .045       0   336.9     .08       0
Bank Sta=316.9,336.9
XS Rating Curve= 0 ,0
Exp/Cntr=0.3,0.1

Type RM Length L Ch R = 1 ,5407    ,293.6,300,306.4
XS GIS Cut Line= 4
     1609497.126      248721.455     1609244.494      248706.434
      1609010.98      248722.821     1608721.478      248587.628
#Sta/Elev= 30
    10.1  924.78    20.2  918.41    30.4  905.89    40.5   899.5   101.2  866.35
   111.4  856.02   172.1  824.97   182.2  815.63   192.3  810.41   253.1  782.63
   262.8  774.36   272.6  769.21   301.8  756.03   330.9  745.02   340.9  743.26
   350.9   743.8   477.4  755.86   497.2  756.17   537.1  750.71   547.1  751.25
   557.1  754.22     567   759.7     577   769.1     617  789.96   656.9  812.93
   666.9  823.35   726.8  855.23   736.8  861.25   746.8   869.3   806.7  899.99
#Mann= 3 , 0 , 0
       0     .08       0   330.9    .045       0   350.9     .08       0
Bank Sta=330.9,350.9
XS Rating Curve= 0 ,0
Exp/Cntr=0.3,0.1

Type RM Length L Ch R = 1 ,5106.9  ,308.1,304.3,300.5
XS GIS Cut Line= 4
     1609465.718      248470.189     1609251.322      248434.684
     1609034.195      248381.426      1608810.24      248310.416
#Sta/Elev= 30
     9.9  867.58    19.8   862.5    29.6  852.84    98.8  817.09   118.5  802.01
   167.9  776.67   187.7  761.71   207.4  752.34   217.3  749.15     227  747.56
   275.6   746.3   295.1  740.12   304.5  738.24   314.5  737.81   324.5  738.35
     334  739.72   343.7  743.45   353.4  749.04   411.7  768.63   421.4  774.62
   431.2  778.83   499.6  804.22   509.4  810.82   577.9  835.52   587.7  840.73
   607.3  855.03   636.7  878.67   656.2  892.21     666  902.37   675.8  908.71
#Mann= 3 , 0 , 0
       0     .06       0   304.5    .045       0   324.5     .06       0
Bank Sta=304.5,324.5
XS Rating Curve= 0 ,0
Exp/Cntr=0.3,0.1

Type RM Length L Ch R = 1 ,4802.6  ,376.7,366.6,356.5
XS GIS Cut Line= 4
     1609603.641      248251.696     1609355.106      248134.256
     1609051.947      248116.504     1608833.455      248138.353
#Sta/Elev= 30
     9.8   828.3    39.3   820.9    98.2  802.89   127.6  792.04   147.3  782.12
   176.7  772.02   186.5  769.96   274.9  756.46   295.1  753.08   305.3  750.02
   335.6   745.6   355.9  744.31   457.1  744.14   467.2  742.91   477.5  739.45
   487.5  737.19   497.5  738.58   507.7  744.85     528  761.06   538.1  774.23
   568.4  795.66   598.5  815.01   608.5  823.57   658.4  840.94   678.4  851.25
   688.4   861.4   698.3  869.48   748.2  898.03   768.2  914.18   798.1  931.38
#Mann= 3 , 0 , 0
       0     .06       0   477.5    .045       0   497.5     .06       0
Bank Sta=477.5,497.5
XS Rating Curve= 0 ,0
Exp/Cntr=0.3,0.1

Type RM Length L Ch R = 1 ,4436.1  ,315.4,317.4,319.4
XS GIS Cut Line= 4
     1609494.395       247623.53     1609218.217      247695.538
     1608928.373      247833.803     1608782.929      247892.549
#Sta/Elev= 30
     9.8  862.56    29.5  853.22    68.9  839.08    88.6  827.32   137.8  807.43
   147.6   802.2   157.5  792.48   196.8  761.65   206.7  754.68   226.4  746.23
   255.9  740.44   295.4  737.23   345.6  736.91   415.9  738.85     446  736.87
     456   734.8     466  735.63   486.1  744.99   536.3  775.55   546.3  784.98
   556.4  792.35   586.5  810.26   596.5  815.71   616.3  822.93   626.2  830.86
   655.6  850.49   694.8  873.18   704.6  882.87   724.2  893.15   763.4  910.75
#Mann= 3 , 0 , 0
     9.8     .06       0     446    .045       0     466     .06       0
#XS Ineff= 2 , 0
       0     415                       0
Permanent Ineff=
       F       F
Bank Sta=446,466
XS Rating Curve= 0 ,0
Exp/Cntr=0.3,0.1

Type RM Length L Ch R = 1 ,4118.7  ,26.4,26.3,26.3
XS GIS Cut Line= 4
     1609480.739      247596.218     1609132.185      247415.936
      1608837.22      247522.451     1608711.918      247738.239
#Sta/Elev= 30
    10.1  848.68    90.6  822.27   130.8  817.96   140.9   814.7     161  803.41
   181.1  785.58   201.2  774.05   211.3  766.25   231.4  756.89   241.5  753.86
   271.7  750.15   382.4  742.03   422.8  736.14   453.1  733.48   544.2  732.96
   635.3  729.36   645.3  727.58   655.3  727.68     706  740.78     726  750.25
     736  751.11   765.9  765.86   785.9  773.89   805.8   787.2   815.8   791.8
   835.8   799.2   845.8  799.05   895.7  825.98   915.6  830.92   955.6     833
#Mann= 3 , 0 , 0
    10.1     .06       0   635.3    .045       0   655.3     .06       0
#XS Ineff= 2 , 0
       0     605             665       0
Permanent Ineff=
       F       F
Bank Sta=635.3,655.3
XS Rating Curve= 0 ,0
Exp/Cntr=0.3,0.1