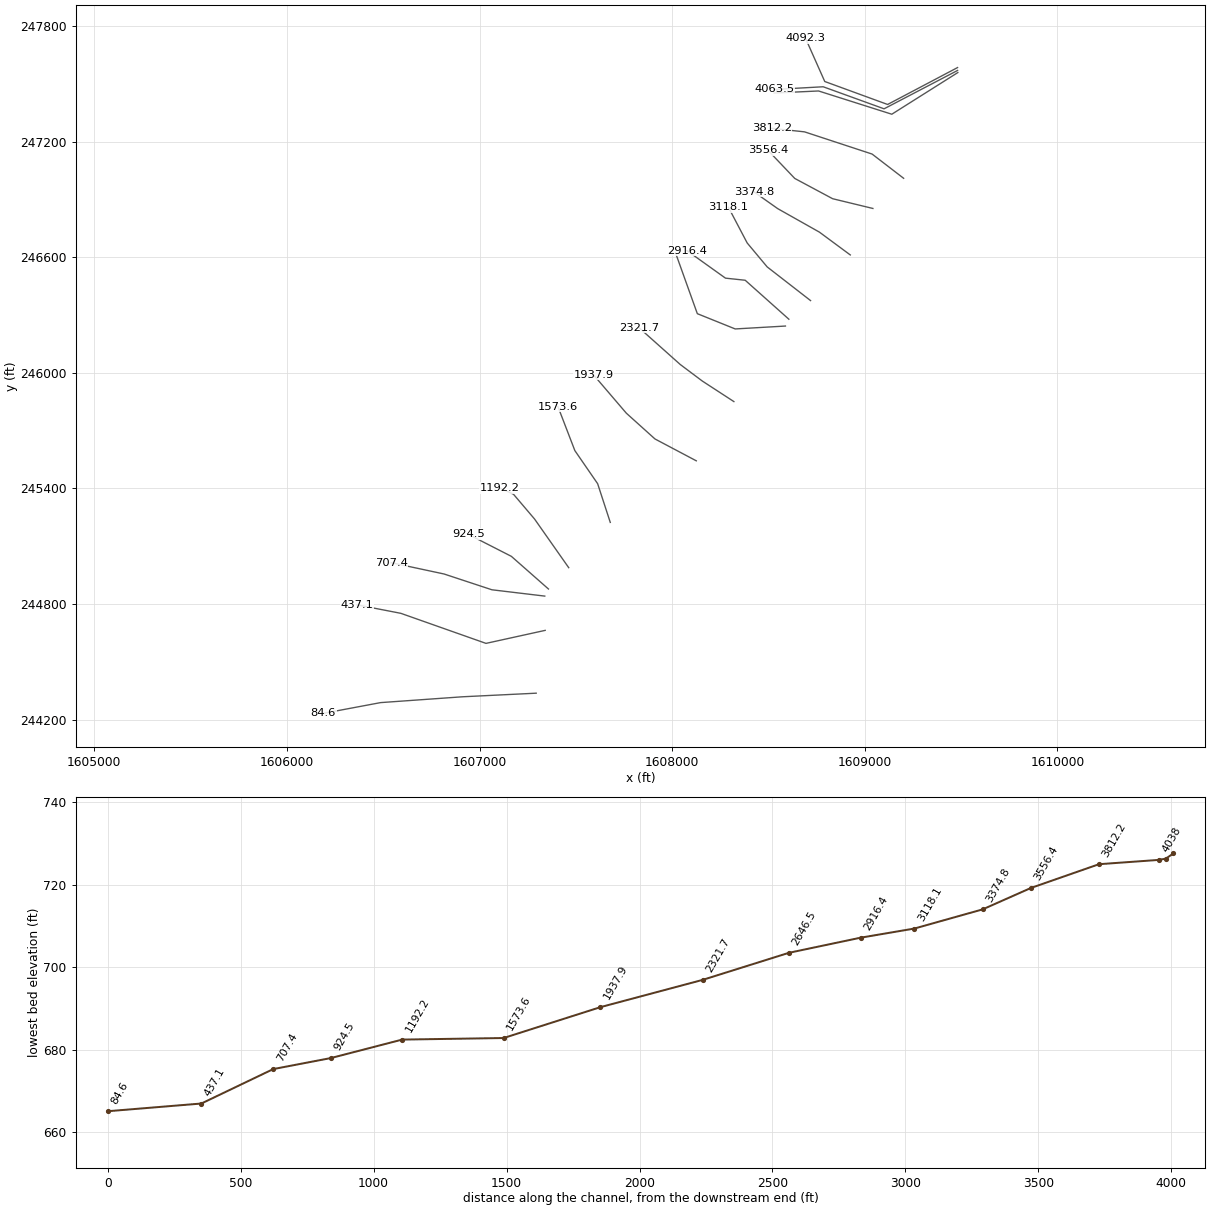
HEC-RAS study sycmrcrk.prj: sycmrcrk

--- sycmrcrk.g01 (geometry) --- (continued)

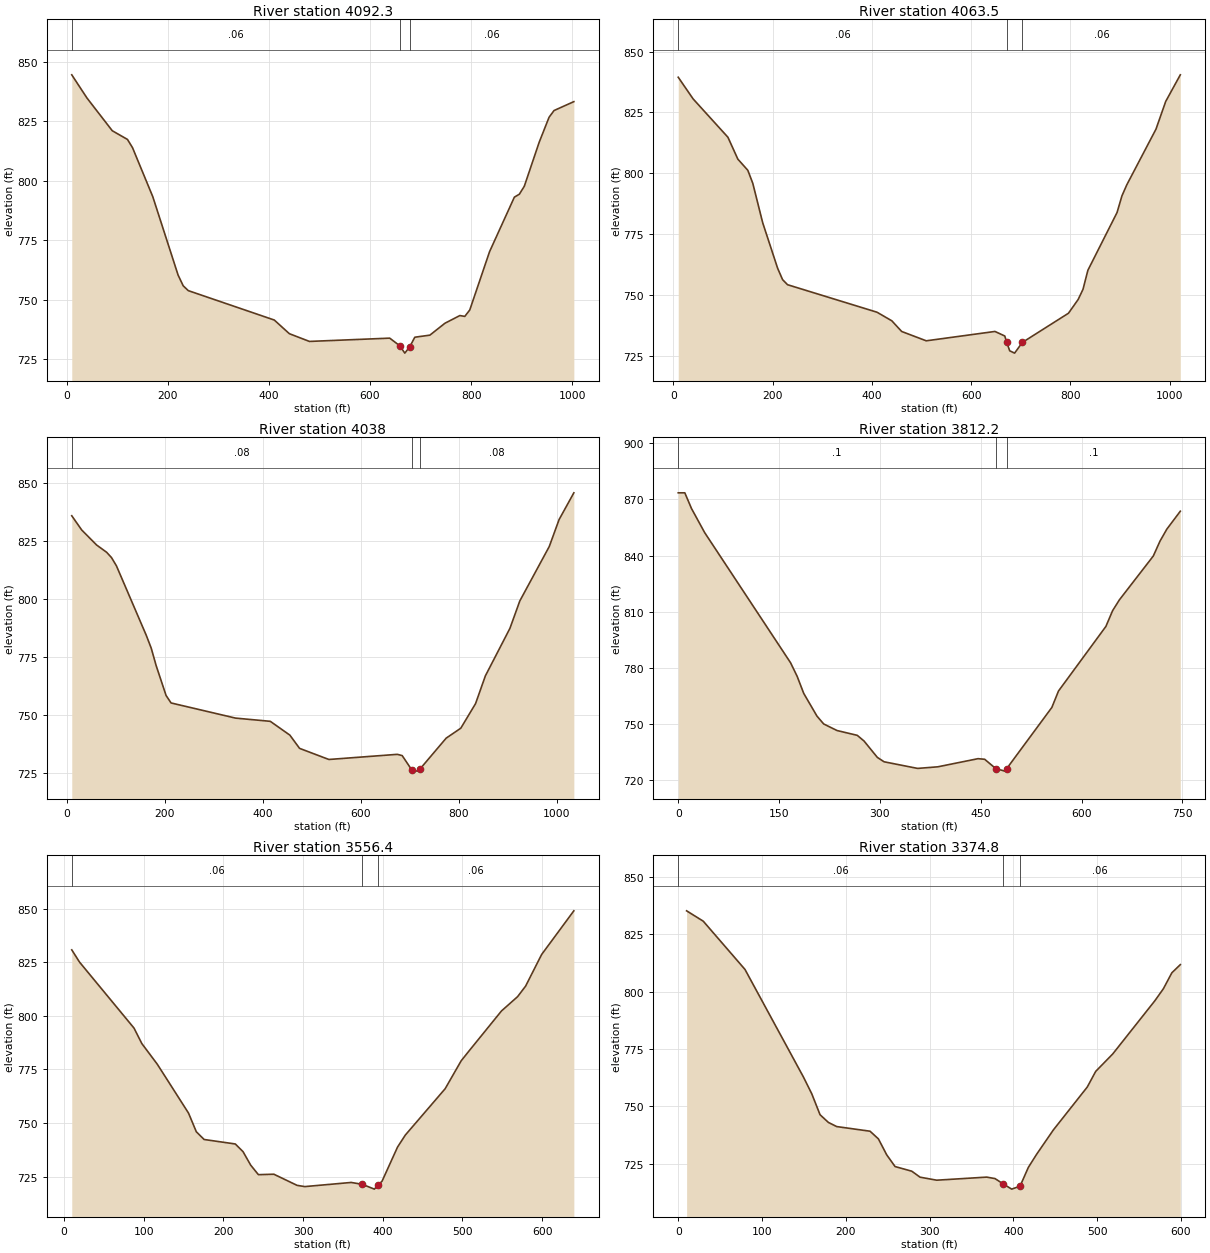
Type RM Length L Ch R = 1 ,4092.3  ,28.8,28.8,28.9
XS GIS Cut Line= 4
     1609482.105      247583.928     1609118.871       247392.38
     1608792.488      247511.552     1608692.801      247735.507
#Sta/Elev= 30
      10  844.61    40.1  834.85    90.1   821.1   120.2  817.44   130.2  813.96
   170.3  793.34   220.3  760.42   230.4   755.9   240.4  753.86   410.6  741.49
   440.4  735.75   480.1  732.49     639  733.87   658.8  730.67   668.8  727.57
   678.8  730.32   688.6  734.26   718.4  735.13   748.2  740.14   777.7  743.37
   787.5  743.02   797.3  745.71   836.5  770.25   885.6  793.18   895.4   794.4
   905.2  797.75   934.6  816.23   954.2  826.76     964  829.59  1003.2  833.33
#Mann= 3 , 0 , 0
      10     .06       0   658.8    .045       0   678.8     .06       0
#XS Ineff= 2 , 0
       0     629                       0
Permanent Ineff=
       F       F
Bank Sta=658.8,678.8
XS Rating Curve= 0 ,0
Exp/Cntr=0.3,0.1

Type RM Length L Ch R = 1 ,4063.5  ,24.7,25.5,26.4
XS GIS Cut Line= 4
     1609482.105      247568.907     1609100.436      247369.847
     1608784.294      247484.241     1608529.965      247470.217
#Sta/Elev= 30
      10  839.45      40  830.56   110.1  814.84   130.1  805.86   150.2  801.28
   160.2  795.94   180.2  779.74   210.2  761.13   220.2  756.44   230.2  754.36
   410.4  743.08   440.3  739.55   460.1  735.18   509.6  731.35     648  735.19
   667.8  733.33  671.39  730.94   677.7  727.26   687.6   726.3  703.22  730.69
   796.1  742.66   815.6  748.29   825.4  752.48   835.2  760.27     894  783.98
   903.8   790.8   913.6  795.33   972.4  818.16     992  829.53  1021.4  840.44
#Mann= 3 , 0 , 0
      10     .06       0  671.39    .045       0  703.22     .06       0
#XS Ineff= 2 , 0
       0     648                       0
Permanent Ineff=
       F       F
Bank Sta=671.39,703.22
XS Rating Curve= 0 ,0
Exp/Cntr=0.3,0.1

Type RM Length L Ch R = 1 ,4038    ,226.1,225.8,225.5
XS GIS Cut Line= 4
      1609483.47      247557.982     1609140.635       247341.81
     1608760.406      247462.408     1608529.965      247451.782
#Sta/Elev= 30
    10.1  835.87    30.4  829.75    60.8  823.29    81.1  820.19    91.2  817.88
   101.3  814.31   162.1  784.47   172.3   778.9   182.4  771.36   202.6  758.54
   212.8  755.33   344.5  748.81   415.3  747.43   455.2   741.5   475.1  735.79
   534.9  731.01   674.6  733.22   684.5  732.69   704.4  726.42   714.4     726
  721.34  727.02   774.3  740.19   804.2  744.48   834.3  755.05   854.3  766.97
   904.5  787.46   924.6  799.22   984.7  822.63  1004.8  834.24  1034.9  845.74
#Mann= 3 , 0 , 0
    10.1     .08       0   704.4    .045       0  721.34     .08       0
#XS Ineff= 2 , 0
       0     672                       0
Permanent Ineff=
       F       F
Bank Sta=704.4,721.34
XS Rating Curve= 0 ,0
Exp/Cntr=0.3,0.1

Type RM Length L Ch R = 1 ,3812.2  ,259.3,255.8,252.3
XS GIS Cut Line= 4
     1609202.043      247009.393     1609038.367      247135.097
     1608687.445      247250.325     1608517.222      247268.656
#Sta/Elev= 30
       0  873.55     9.8  873.55    19.7  865.19    39.3  852.32   167.1  782.82
   176.9  775.58   186.7  766.45   206.4  754.32   216.4  750.13   236.3  746.62
   266.3  744.06   276.3  741.07   296.2  732.29   306.2  729.94   356.1   726.4
   386.1  727.25     446   731.6   455.9  731.27  472.35  726.31   485.9  724.95
  488.78  726.35   555.8  758.95   565.7  767.73   636.2  802.21   646.2  810.64
   656.3  816.41   706.7   839.8   716.7  847.76   726.8  854.13   746.9  863.73
#Mann= 3 , 0 , 0
       0      .1       0  472.35    .045       0  488.78      .1       0
#XS Ineff= 2 , 0
       0     446                       0
Permanent Ineff=
       F       F
Bank Sta=472.35,488.78
XS Rating Curve= 0 ,0
Exp/Cntr=0.3,0.1

Type RM Length L Ch R = 1 ,3556.4  ,182,181.6,181.2
XS GIS Cut Line= 4
     1609042.389      246852.888     1608833.455      246903.415
     1608636.812      247008.564     1608497.523      247154.681
#Sta/Elev= 30
     9.8  830.74    19.5  825.05    87.9  794.27    97.7  787.07   117.2  777.38
   156.3  754.64   166.1  745.92   175.9  742.33     215  740.24   224.7  736.66
   234.3  730.38     244  725.93   263.4  726.14   292.5  720.95   302.2  720.37
   360.4   722.3  374.48  721.42   389.5  719.19  394.09  721.01   399.2  722.93
   418.6  738.81   428.3  744.37   478.3  765.99   498.5  779.06   508.6  783.75
     549  802.26   569.2  808.91   579.3  813.85   599.4  828.59   639.8  848.94
#Mann= 3 , 0 , 0
     9.8     .06       0  374.48    .045       0  394.09     .06       0
Bank Sta=374.48,394.09
XS Rating Curve= 0 ,0
Exp/Cntr=0.3,0.1

Type RM Length L Ch R = 1 ,3374.8  ,264.1,256.8,249.5
XS GIS Cut Line= 4
     1608925.041      246611.677     1608764.813      246730.027
     1608548.141      246852.019     1608424.329      246939.416
#Sta/Elev= 30
      10  835.15    29.9  830.63    79.7  809.63   149.4  762.85   159.4  755.52
   169.3  746.39   179.3  743.03   189.2  741.23     229  739.21     239  735.86
   248.9  728.92   258.9  723.82   278.8  721.81   288.7   719.2   308.6  717.89
   368.3  719.23   378.2  718.59   388.1  716.23   398.1     714   408.1  715.29
     418  723.48     428  729.24   447.9  739.79   488.3  758.43   498.4  765.26
   518.6  772.79   569.1  796.04   579.2  801.24   589.3  808.17   599.4  811.72
#Mann= 3 , 0 , 0
       0     .06       0   388.1    .045       0   408.1     .06       0
Bank Sta=388.1,408.1
XS Rating Curve= 0 ,0
Exp/Cntr=0.3,0.1

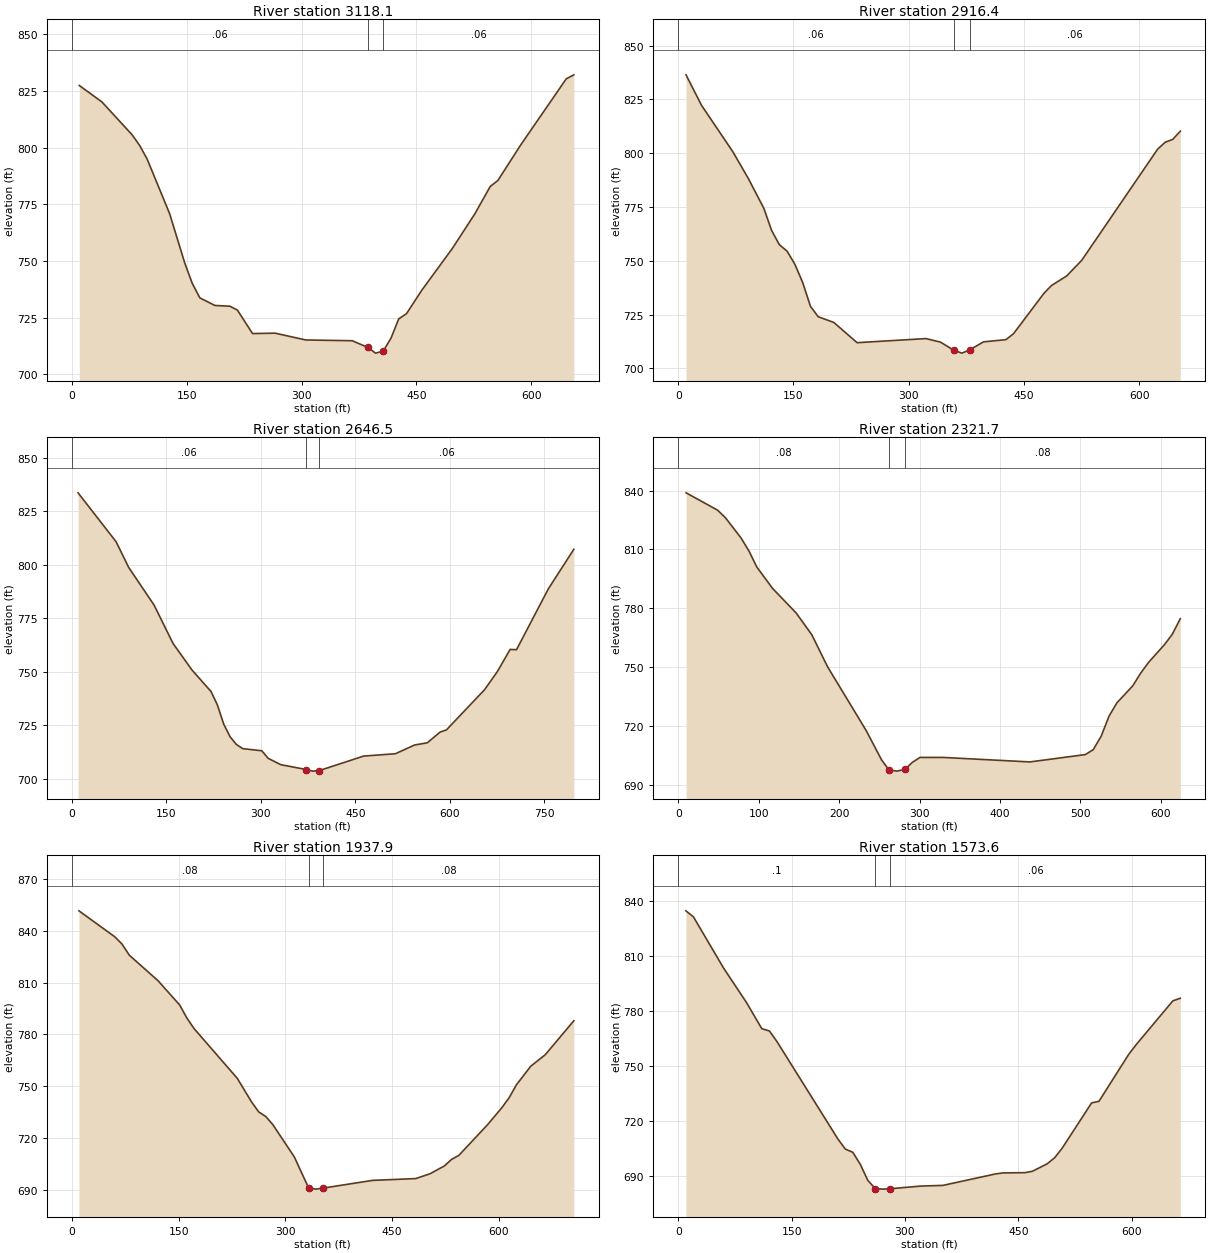
Type RM Length L Ch R = 1 ,3118.1  ,185.4,201.7,218
XS GIS Cut Line= 4
     1608718.747      246374.936     1608493.426       246549.73
     1608389.642      246673.998     1608292.686      246858.351
#Sta/Elev= 30
     9.8  827.37    39.3  820.14    78.7  805.65    88.5  800.99    98.3     795
   127.8   770.8   147.5  749.07   157.3   740.1   167.2  733.72   186.8  730.37
   206.5  730.04   216.3  728.29     236  717.97   265.5  718.15   305.4  715.15
   366.1  714.82   386.5  711.86   396.5  709.35   406.5  710.21   416.7  715.92
   426.8  724.46     437  726.77     457  737.13   496.7  755.45   526.4   770.9
   546.3  782.86   556.2  785.46   585.9  801.08   645.5  830.31   655.4  832.07
#Mann= 3 , 0 , 0
       0     .06       0   386.5    .045       0   406.5     .06       0
Bank Sta=386.5,406.5
XS Rating Curve= 0 ,0
Exp/Cntr=0.3,0.1

Type RM Length L Ch R = 1 ,2916.4  ,275.3,270,264.6
XS GIS Cut Line= 4
     1608606.086      246278.321       1608379.4      246480.427
     1608276.982      246491.352     1608076.242      246634.737
#Sta/Elev= 30
    10.1  836.43    30.4  822.22    70.9   800.8    91.1  788.34   111.4  774.43
   121.5  764.15   131.6  757.51   141.7   754.5   151.8  748.42     162  739.93
   172.1  728.88   182.2  724.04   202.5  721.39   232.8  711.99   322.4   713.9
   341.2  712.27   359.2  708.37   369.2  707.14   379.2  708.64   397.3  712.38
   426.4  713.39   436.3  716.14   475.8  734.86   485.6  738.52   505.4  742.96
   525.1  750.25   623.8  801.85   633.7  805.11   643.5  806.43   653.4  810.25
#Mann= 3 , 0 , 0
       0     .06       0   359.2    .045       0   379.2     .06       0
Bank Sta=359.2,379.2
XS Rating Curve= 0 ,0
Exp/Cntr=0.3,0.1

Type RM Length L Ch R = 1 ,2646.5  ,330.8,324.7,317.3
XS GIS Cut Line= 4
     1608588.334      246242.816     1608327.508      246227.795
     1608130.865      246306.998     1608021.619      246611.522
#Sta/Elev= 30
      10  833.56    70.3  810.72    90.4  798.66   130.6  781.11   160.8  763.11
   190.9   750.7   221.1  740.66   231.1   734.4   241.2  725.42   251.2  719.55
   261.3  715.92   271.4  713.98   301.6  712.99   311.7  709.44   331.9  706.47
   372.4  704.21   382.4  703.47   392.4  703.68   463.2   710.5   513.7  711.61
     544  715.68   564.2  716.71   584.5  721.71   594.6  722.75   655.2  741.56
   675.5  750.04   695.7  760.36   705.8  760.23   756.3  788.65   796.8  807.18
#Mann= 3 , 0 , 0
       0     .06       0   372.4    .045       0   392.4     .06       0
Bank Sta=372.4,392.4
XS Rating Curve= 0 ,0
Exp/Cntr=0.3,0.1

Type RM Length L Ch R = 1 ,2321.7  ,385.6,383.8,382
XS GIS Cut Line= 4
      1608320.68      245850.895     1608156.811       245957.41
     1608042.102      246043.442     1607829.072      246233.257
#Sta/Elev= 30
     9.8  838.82    48.9  829.98    58.6  826.17    78.2  815.74      88   809.1
    97.7  800.99   117.3  790.06   146.6  777.56   166.1  766.43   185.7  750.09
   233.7  717.57   252.8  702.63   261.9  697.56   271.9   696.9   281.9  697.78
     291  701.35   300.6   703.9   329.3  703.89   437.2  701.59   506.1  705.33
   515.9  707.82   525.8   714.7   535.6  724.95   545.4  731.73   565.1   740.4
     575  746.91   584.8  752.38   604.5  761.39   614.3  766.73   624.2  774.67
#Mann= 3 , 0 , 0
       0     .08       0   261.9    .045       0   281.9     .08       0
Bank Sta=261.9,281.9
XS Rating Curve= 0 ,0
Exp/Cntr=0.3,0.1

Type RM Length L Ch R = 1 ,1937.9  ,369.1,364.3,359.6
XS GIS Cut Line= 4
     1608125.403       245543.64     1607911.007      245656.983
     1607762.159       245790.81     1607591.461      245990.184
#Sta/Elev= 30
    10.1  851.65    60.6  836.54    70.7  832.32    80.8  825.94   121.3  811.07
   151.6  797.04   161.7  789.45   171.8  783.36   232.4  754.56   252.5  740.87
   262.5  735.08   272.5   732.4   282.5  727.62   312.6  708.94   332.6     691
   342.6   690.3   352.6  690.88   422.7  695.38   483.1  696.41   503.2  699.23
   523.4  703.77   533.5  707.58   543.6  709.86     584  727.69   604.2  737.61
   614.3  743.33   624.4  750.75   644.6  761.57   664.8  768.16   705.1  787.93
#Mann= 3 , 0 , 0
       0     .08       0   332.6    .045       0   352.6     .08       0
Bank Sta=332.6,352.6
XS Rating Curve= 0 ,0
Exp/Cntr=0.3,0.1

Type RM Length L Ch R = 1 ,1573.6  ,379.3,381.4,383.5
XS GIS Cut Line= 4
     1607678.858      245224.095     1607613.311      245424.835
     1607494.985       245596.58     1607407.108      245824.949
#Sta/Elev= 30
    10.1  834.83    20.1  831.54    60.3  803.38    90.5  784.63   110.6  770.44
   120.7  769.19   130.7  763.37   211.2  710.26   221.1   704.7     231  702.93
     241   696.3   250.9  687.56   260.8  683.09   270.8  682.81   280.8  683.03
   320.4  684.46   350.2  684.85   419.7  691.09   429.5  691.66   458.9  691.81
   468.7  692.57   488.2  696.63     498   699.9   507.8  705.01     547   729.9
   556.8   730.8   595.9  756.29   605.7  761.58   654.6  785.67   664.4  787.08
#Mann= 3 , 0 , 0
       0      .1       0   260.8    .045       0   280.8     .06       0
Bank Sta=260.8,280.8
XS Rating Curve= 0 ,0
Exp/Cntr=0.3,0.1

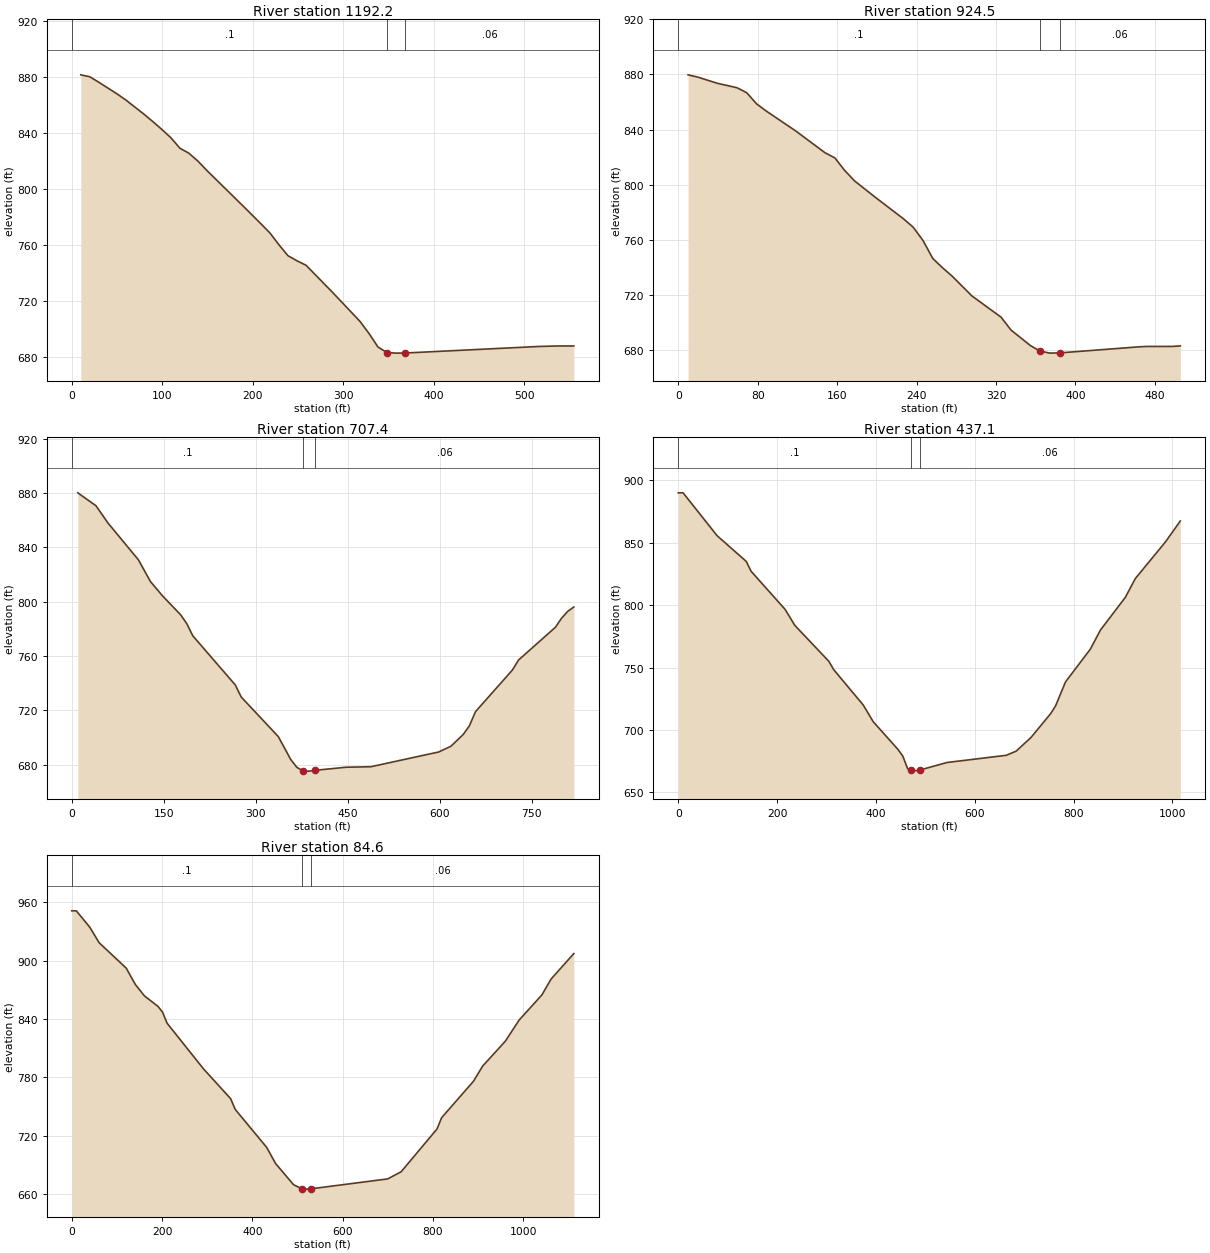
Type RM Length L Ch R = 1 ,1192.2  ,259.9,267.7,275.6
XS GIS Cut Line= 4
     1607463.097      244989.215     1607285.572      245241.847
     1607176.326      245370.212     1607105.795      245402.668
#Sta/Elev= 30
      10  881.76    19.9  880.36    29.9  876.44    49.8  868.21    59.8  863.72
    79.7  853.63    89.6  848.29    99.6  842.64   109.6  836.68   119.5   829.2
   129.5  825.59   139.4  820.01   149.4  813.22   189.2  787.92   209.2  775.02
   219.1  768.47   229.1  759.98     239   752.2     249  748.54     259  745.36
   288.8   725.6   318.7   705.1   328.6  696.48   338.5   686.8   348.3  682.87
   358.3  682.43   368.3   682.5   516.1   687.2   535.6  687.54     555  687.56
#Mann= 3 , 0 , 0
       0      .1       0   348.3    .045       0   368.3     .06       0
Bank Sta=348.3,368.3
XS Rating Curve= 0 ,0
Exp/Cntr=0.3,0.1

Type RM Length L Ch R = 1 ,924.5   ,214,217.1,220.2
XS GIS Cut Line= 4
     1607357.948      244878.603     1607165.401      245047.935
     1606981.527      245141.842     1606944.657      245163.691
#Sta/Elev= 30
     9.9  879.74    19.7  878.09    39.4   873.6    59.2  870.38      69  866.75
    78.9  858.72    88.8   853.4   118.3  839.07   147.9  823.21   157.8  819.49
   167.7  810.37   177.5   802.9   197.2  791.67   226.8  775.38   236.7  769.25
   246.6  759.55   256.4  746.58   266.2  739.87   276.1  733.64   295.7  719.49
   325.2  704.01   335.1  694.73   354.7  683.46   364.4   679.4   374.4  677.96
   384.4  678.14   462.9  682.46   471.4  682.81   497.2  682.81   505.7  683.17
#Mann= 3 , 0 , 0
       0      .1       0   364.4    .045       0   384.4     .06       0
Bank Sta=364.4,384.4
XS Rating Curve= 0 ,0
Exp/Cntr=0.3,0.1

Type RM Length L Ch R = 1 ,707.4   ,270.7,270.3,269.9
XS GIS Cut Line= 4
     1607338.829      244841.733     1607064.348      244874.507
     1606815.813      244956.441     1606541.332      245015.161
#Sta/Elev= 30
     9.9  880.27    39.5  870.75    59.2  857.94   108.6  830.98   128.3  814.95
   148.1  804.32   177.7  790.38   187.6  783.88   197.5  774.89   266.6   738.8
   276.4  729.85   336.8  700.73     357  683.93     367  678.12   377.1  675.36
   387.1  675.28   397.1  675.89   447.5  678.15   487.8  678.51   598.3  689.37
   618.3  693.59   638.4  702.28   648.4   708.6   658.4  719.08   718.6  749.73
   728.6  757.11   788.7  781.23   798.8  787.92   808.8  792.97   818.8  796.16
#Mann= 3 , 0 , 0
       0      .1       0   377.1    .045       0   397.1     .06       0
Bank Sta=377.1,397.1
XS Rating Curve= 0 ,0
Exp/Cntr=0.3,0.1

Type RM Length L Ch R = 1 ,437.1   ,344.2,352.5,360.7
XS GIS Cut Line= 4
     1607340.863      244663.949     1607033.588      244596.442
     1606591.298      244752.407      1606363.17      244796.636
#Sta/Elev= 30
       0  890.06     9.8  890.06    78.7  855.68   137.6  835.09   147.5  827.16
   216.3  796.59     236  783.74   304.8  754.98   314.6  748.31   374.5  719.86
   394.4  706.62   444.3  684.51   454.3  679.07   464.3  668.87  470.13  667.72
   474.3  666.93  489.26  667.86   544.1  673.86   663.8  679.61   683.8  682.94
   713.7  693.84   753.7  713.06   763.6  719.23   783.6   738.4   834.1  764.81
   854.3  779.98   904.8  806.29     925  821.34   985.7  850.58    1016  867.46
#Mann= 3 , 0 , 0
       0      .1       0  470.13    .045       0  489.26     .06       0
Bank Sta=470.13,489.26
XS Rating Curve= 0 ,0
Exp/Cntr=0.3,0.1

Type RM Length L Ch R = 1 ,84.6    ,86.9,84.6,82.3
XS GIS Cut Line= 4
     1607294.306      244338.051      1606912.54      244319.429
     1606486.545      244289.167     1606188.582      244233.298
#Sta/Elev= 30
       0  951.31    10.1  951.31    40.2  934.32    60.4  918.63   120.7  892.36
   140.8  875.59   160.9  863.87   191.1  852.98   201.2  847.04   211.2  835.71
   291.7  788.83     352   758.1   362.1  747.12   431.9  707.95   451.7  691.31
   491.5  669.55  509.98  665.39   521.3  665.06  529.69  665.37     700  675.57
   729.8  682.94   809.3  726.98   819.4  738.51   890.1  776.05   910.3  791.58
   960.9   817.4   991.2  838.96  1041.7  864.86  1061.9   881.1  1112.4  907.38
#Mann= 3 , 0 , 0
       0      .1       0  509.98    .045       0  529.69     .06       0
Bank Sta=509.98,529.69
XS Rating Curve= 0 ,0
Exp/Cntr=0.3,0.1
Stream Node=sycmrcrk        ,Main            , 0 , 0 ,Upstream end
Stream Node=sycmrcrk        ,Main            , 0 , 1 ,Downstream end

Chan Stop Cuts=-1
Use User Specified Reach Order=0